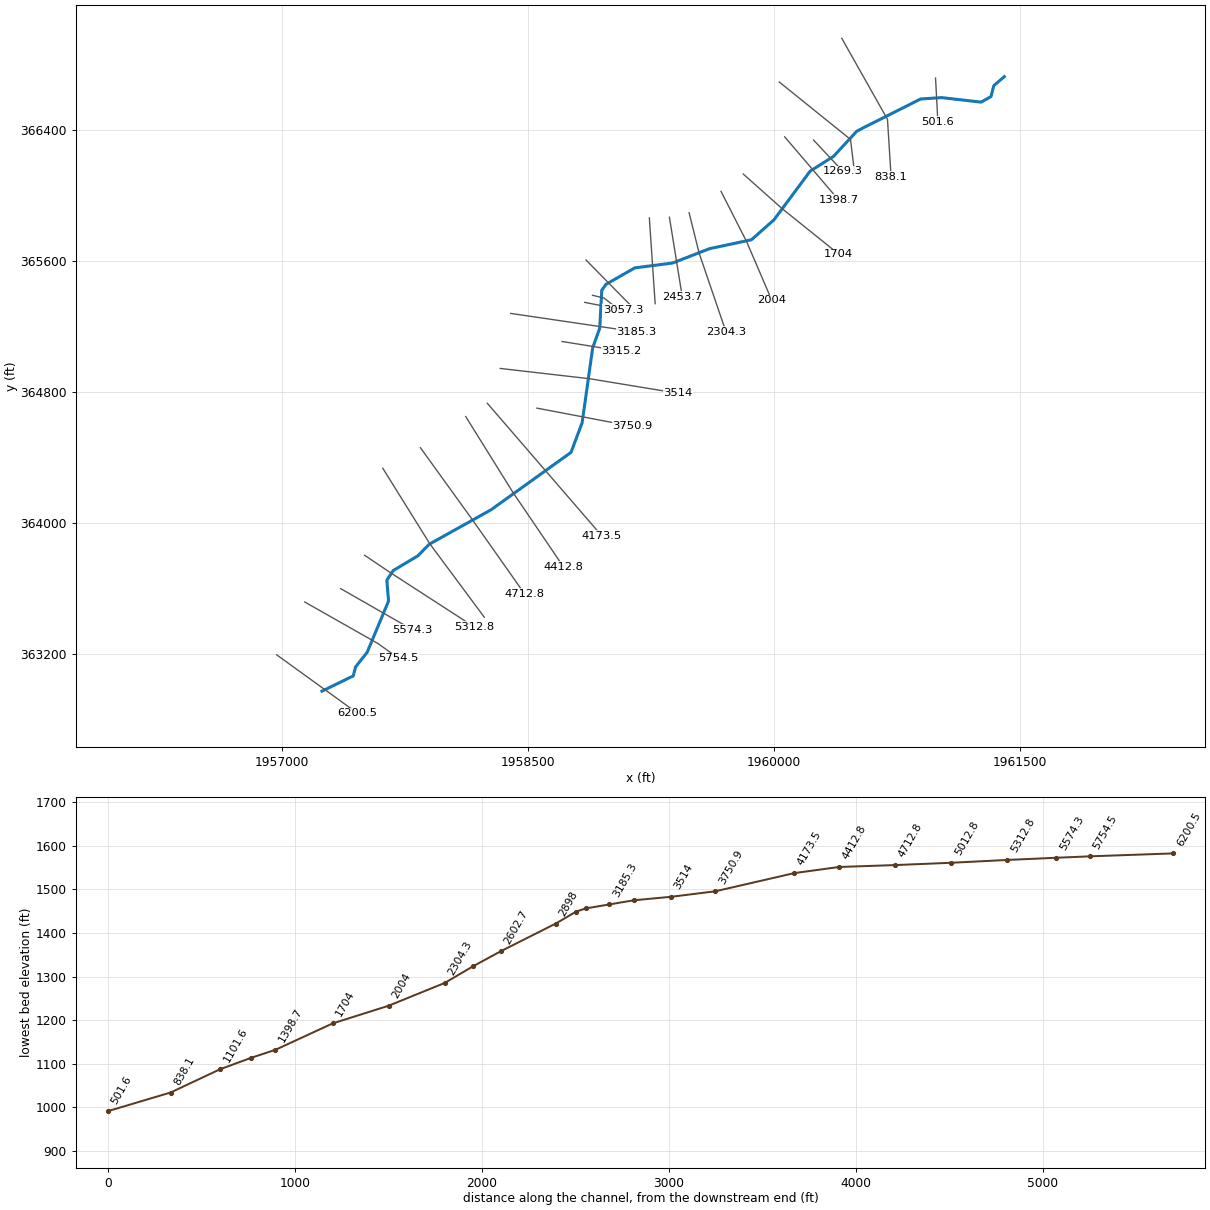
--- CoalRun.prj (project) ---

Proj Title=CoalRun
Current Plan=p01
Default Exp/Contr=0,0
English Units
Geom File=g01
Flow File=f01
Plan File=p01
BEGIN DESCRIPTION:
END DESCRIPTION:
DSS Export Rating Curves= 0
DSS Export Rating Curve Sorted= 0
DSS Export Volume Flow Curves= 0
DXF OffsetX= 0
DXF OffsetY= 0
DXF ScaleX= 0
DXF ScaleY= 0

--- CoalRun.p01 (plan) ---

Plan Title=Floodplain
Program Version=4.00
Geom File=g01
Flow File=f01
K Sum by GR=0
Std Step Tol=0.01
Critical Tol=0.01
Num of Std Step Trials=20
Max Error Tol=0.3
Flow Tol Ratio=0.001
Split Flow NTrial=30
Split Flow Tol=0.02
Split Flow Ratio=0.02
Log Output Level=0
Friction Slope Method=1
Unsteady Friction Slope Method=2
Unsteady Bridges Friction Slope Method=1
Global Log Level=0
CheckData=False
Run HTab=0
Run UNet=0
Run PostProcess=0
UNET Theta=0
UNET Theta Warmup=0
UNET ZTol=0
UNET ZSATol=0
UNET MxIter=0
UNET MaxInSteps=0
UNET DtIC=0
UNET DtMin=0
UNET MaxCRTS=0
UNET WFStab=0
UNET SFStab=0
UNET WFX=0
UNET SFX=0
UNET DSS MLevel=0
UNET DZMax Abort=0
UNET Convert EG Bridges=0
UNET Use Existing IB Tables=0
UNET Froude Limit=0
UNET Froude Power=0
Write IC File=0
Echo Input=False
Echo Output=False
Write Detailed=0

--- CoalRun.f01 (steady flow) ---

Flow Title=NFF Regression Equation
Program Version=4.00
Number of Profiles=1
Profile Names=P100yr
River Rch & RM=CoalRun,Main      ,6200.5
528.5964
River Rch & RM=CoalRun,Main      ,5754.5
529.6042
River Rch & RM=CoalRun,Main      ,5574.3
770.0398
Boundary for River Rch & Prof#=CoalRun,Main      ,1
Up Type=0
Dn Type=3
Dn Slope=0.162201

--- CoalRun.g01 (geometry) ---

Geom Title=USGS 3m DEM
Program Version=4.10

River Reach=CoalRun         ,Main
Reach XY= 30
     1957244.364      362971.801     1957435.538      363065.223
     1957449.225      363119.371     1957520.405      363209.648
     1957650.613      363522.148     1957640.197      363649.579
     1957679.214      363708.643     1957829.433       363798.19
     1957898.877      363869.371     1958275.614       364079.44
     1958763.461      364430.134     1958831.169       364610.69
     1958895.942       365069.76     1958938.808      365188.815
     1958951.156      365420.246     1958976.725      365456.395
      1959152.35      365556.871      1959383.66      365586.721
     1959607.608      365674.008     1959864.155      365728.746
     1960001.308      365850.273     1960222.206      366147.855
     1960364.155      366237.426     1960507.696      366392.656
     1960895.405      366588.121     1961022.616      366596.801
     1961264.457      366569.109     1961325.025      366602.902
     1961342.272      366670.041     1961406.474      366725.075

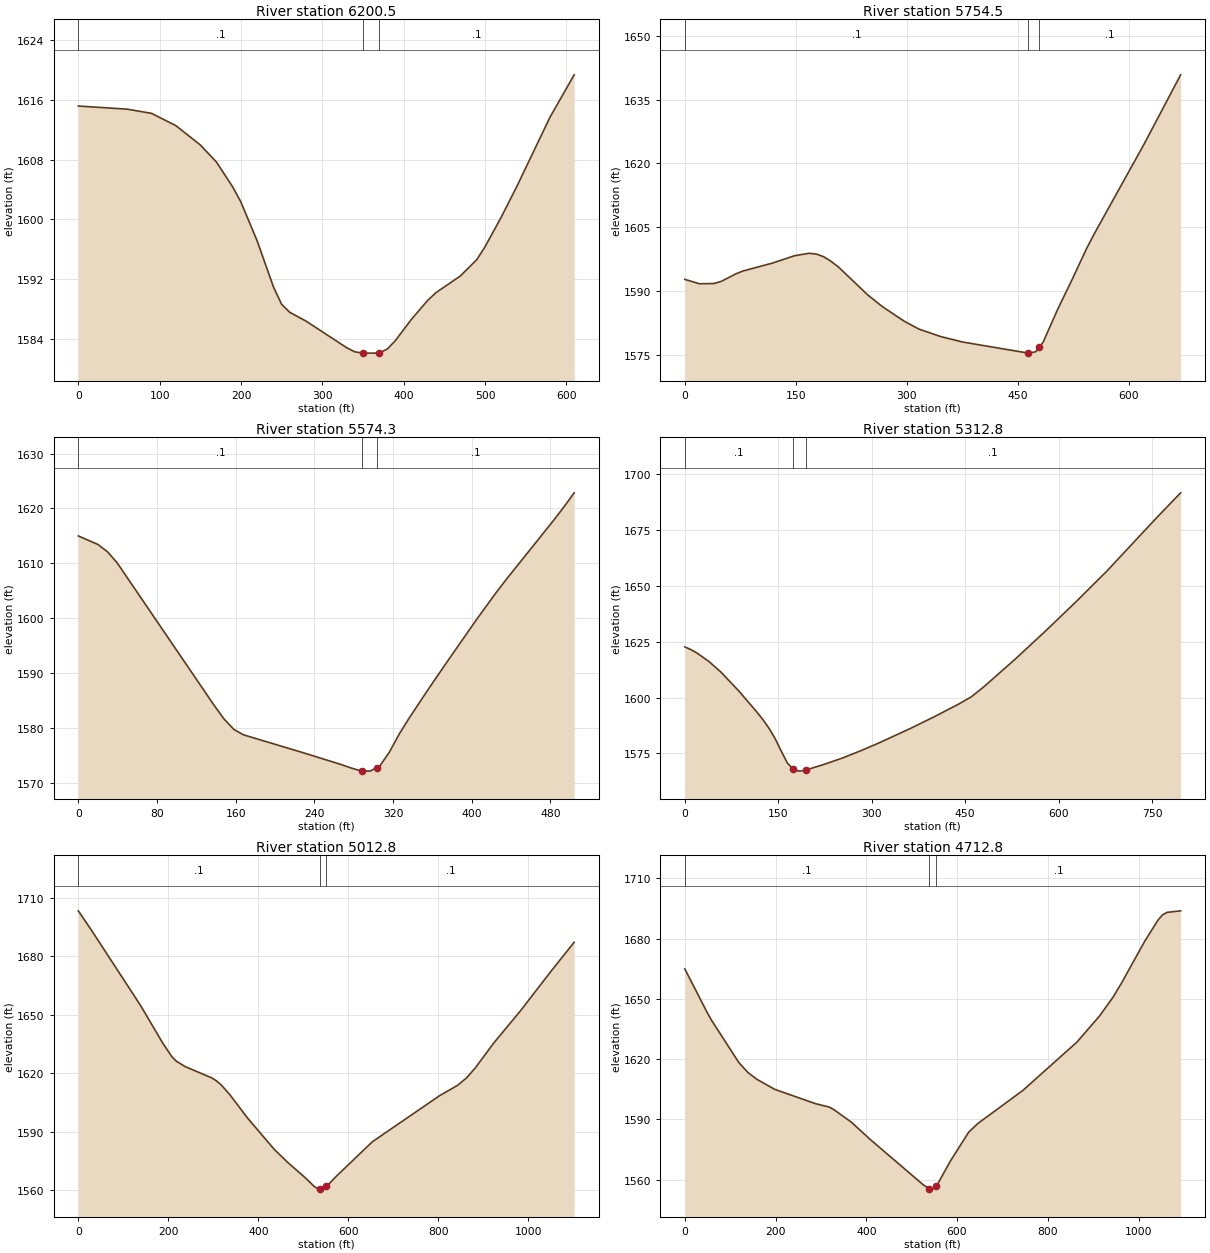
Type RM Length L Ch R = 1 ,6200.5  ,445.7,446.2,446.7
XS GIS Cut Line= 2
     1956968.711      363193.667     1957462.454      362836.291
#Sta/Elev= 30
       0 1615.19      60 1614.77    89.9 1614.21   119.9 1612.56   149.9 1609.98
   169.9 1607.67   189.8 1604.34   199.8 1602.34   219.8 1597.13   239.8 1590.97
   249.8 1588.64   259.8 1587.55   279.8 1586.38   329.7 1582.82   339.7 1582.26
   349.7 1582.09   358.9 1582.08   369.7 1582.09   379.7 1582.62   389.7 1583.75
   409.7 1586.64   429.6 1589.16   439.6 1590.18   469.6 1592.42   489.6 1594.58
   499.6 1596.27   519.6 1600.24   539.6 1604.54   579.5 1613.63   609.5 1619.37
#Mann= 3 , 0 , 0
       0      .1       0   349.7    .045       0   369.7      .1       0
Bank Sta=349.7,369.7
XS Rating Curve= 0 ,0
Exp/Cntr=0.3,0.1

Type RM Length L Ch R = 1 ,5754.5  ,180.1,180.1,180.1
XS GIS Cut Line= 3
     1957139.561      363516.559     1957586.281      363262.634
     1957713.244      363171.723
#Sta/Elev= 30
       0 1592.73    19.8 1591.69    39.5 1591.75    49.4 1592.26    69.2 1594.04
      79 1594.71   118.6 1596.56   148.2 1598.28     168 1598.86   177.9 1598.67
   187.8 1598.03   197.6 1596.97   207.5 1595.65     247  1589.1   266.8 1586.34
   296.4  1582.9   316.2 1581.04   345.9 1579.27   375.5 1577.99     464 1575.39
   464.4 1575.38   474.3 1575.71     479 1576.77   484.2 1577.95     504 1585.74
   523.6 1592.76   543.1 1600.04   552.9  1603.3   621.2 1624.71     670 1640.82
#Mann= 3 , 0 , 0
       0      .1       0     464    .045       0     479      .1       0
Bank Sta=464,479
XS Rating Curve= 0 ,0
Exp/Cntr=0.3,0.1

Type RM Length L Ch R = 1 ,5574.3  ,263.3,261.6,260.4
XS GIS Cut Line= 2
     1957359.003      363598.066     1957796.318      363347.276
#Sta/Elev= 27
       0 1614.98    19.8 1613.44    29.6  1612.1    39.5 1610.07   138.4 1584.01
   148.3 1581.57   158.2  1579.7     168 1578.71   227.4 1575.52   266.9 1573.32
   276.8  1572.7   286.7 1572.17   288.7 1572.16   296.5  1572.1   303.7 1572.76
   306.4 1573.01   316.3 1575.58   326.2 1578.84   336.1  1581.7   355.8 1587.02
   375.6 1592.21   405.3 1599.85     425  1604.7   434.9 1607.01   484.4 1618.09
   494.2 1620.39   504.1 1622.84
#Mann= 3 , 0 , 0
       0      .1       0   288.7    .045       0   303.7      .1       0
Bank Sta=288.7,303.7
XS Rating Curve= 0 ,0
Exp/Cntr=0.3,0.1

Type RM Length L Ch R = 1 ,5312.8  ,309.3,299.7,291.5
XS GIS Cut Line= 3
     1957504.775      363801.833     1957665.358      363693.402
     1958170.592      363366.182
#Sta/Elev= 30
       0 1622.65     9.7 1621.48    19.4 1619.95    38.8 1616.13    58.1 1611.38
    87.2  1602.8   116.3 1593.31     126 1589.92   135.6 1586.08   145.3 1581.47
     155 1575.93   164.7 1570.69   174.4 1567.85   184.1  1567.1   193.8 1567.55
   223.4  1570.1     253 1572.96   282.6 1576.24   312.2 1579.78   361.5 1586.12
     401 1591.51   440.5 1597.24   460.2 1600.42   479.9 1604.82   529.3 1616.96
   578.6 1629.69     628 1642.91   677.3 1656.57   756.2 1680.15   795.7 1691.59
#Mann= 3 , 0 , 0
       0      .1       0   174.4    .045       0   193.8      .1       0
Bank Sta=174.4,193.8
XS Rating Curve= 0 ,0
Exp/Cntr=0.3,0.1

Type RM Length L Ch R = 1 ,5012.8  ,298.5,300,299.4
XS GIS Cut Line= 3
     1957615.543      364333.232      1957902.67      363871.495
     1958234.759      363423.276
#Sta/Elev= 30
       0 1703.25    29.7 1693.13   138.4 1654.69   187.8 1635.37   207.6 1628.56
   217.5 1626.23   237.3 1623.43   296.6  1617.6   306.5 1616.16   316.4 1614.28
   336.1  1609.2   375.7 1597.13     435 1581.08   464.6 1574.43   504.2 1566.44
     524    1562   533.8 1560.62   536.2 1560.64   543.7 1560.71   551.2 1561.97
   573.6 1567.31   653.3  1584.9   802.7 1608.52   842.6 1613.83   862.5 1617.61
   882.4 1622.88   922.3 1635.32     982 1651.91  1051.8 1672.75  1101.6 1687.15
#Mann= 3 , 0 , 0
       0      .1       0   536.2    .045       0   551.2      .1       0
Bank Sta=536.2,551.2
XS Rating Curve= 0 ,0
Exp/Cntr=0.3,0.1

Type RM Length L Ch R = 1 ,4712.8  ,301.5,300,299.6
XS GIS Cut Line= 3
     1957845.393      364458.227     1958164.619      364015.035
     1958479.066      363568.067
#Sta/Elev= 30
       0 1664.91    49.6 1643.08    59.6 1639.12   119.2 1618.29     139  1613.4
   158.9 1609.97   198.6 1604.95     288 1597.87   317.8 1596.21   327.7 1595.03
   367.4 1588.62   407.2 1580.35   526.3 1557.36   538.7 1555.64   546.2 1555.36
   553.7 1556.93   556.1 1557.43   585.9 1569.54   625.7 1583.69   645.6 1587.96
   744.9 1604.43   864.2  1628.5   913.8 1641.43   943.6 1650.77   963.5 1658.25
  1013.2 1678.51    1043 1689.22  1052.9 1691.79  1062.9 1693.02  1092.7 1693.78
#Mann= 3 , 0 , 0
       0      .1       0   538.7    .045       0   553.7      .1       0
Bank Sta=538.7,553.7
XS Rating Curve= 0 ,0
Exp/Cntr=0.3,0.1

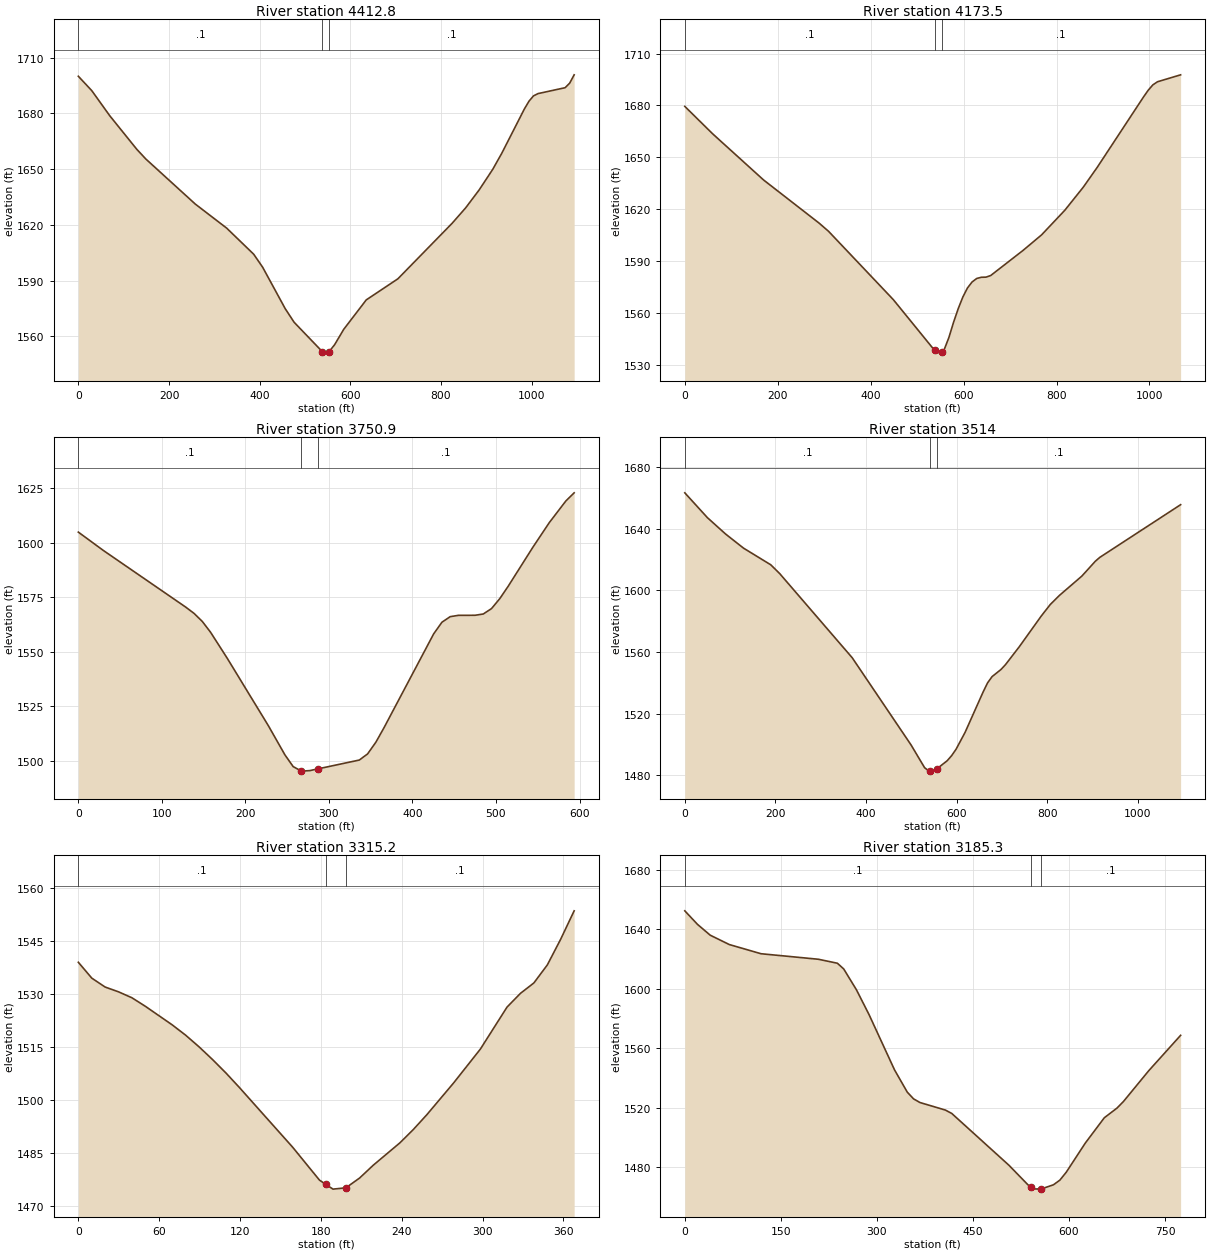
Type RM Length L Ch R = 1 ,4412.8  ,235.7,239.2,241.9
XS GIS Cut Line= 3
     1958121.395      364648.792     1958409.415      364185.619
     1958717.024      363731.846
#Sta/Elev= 30
       0 1700.06    29.8 1692.26    69.4 1678.77   128.9 1660.74   148.8 1655.52
   257.8 1631.27   327.2 1618.28   386.8 1604.23   406.6 1597.21   456.2 1574.96
     476 1567.58   537.9 1551.84   545.4 1550.98   552.9  1551.7   565.4 1555.57
   585.3 1563.77   635.1 1579.65   704.9 1591.01   824.5  1620.9   854.4 1629.22
   884.3 1638.93   914.2    1650   934.2  1658.7     984 1682.52     994 1686.62
  1003.9 1689.48  1013.9 1690.71  1073.7 1693.89  1083.7 1696.33  1093.6 1700.82
#Mann= 3 , 0 , 0
       0      .1       0   537.9    .045       0   552.9      .1       0
Bank Sta=537.9,552.9
XS Rating Curve= 0 ,0
Exp/Cntr=0.3,0.1

Type RM Length L Ch R = 1 ,4173.5  ,407.3,422.5,437.7
XS GIS Cut Line= 2
     1958253.239      364729.774     1958950.149      363921.742
#Sta/Elev= 30
       0 1679.47    59.8 1663.66   169.5 1636.96   289.2 1611.99   309.2 1607.34
   448.8  1567.8   537.7 1538.46   548.5 1536.92   552.7 1537.85   558.5 1539.14
   568.4 1546.01   578.4 1554.77   588.4  1562.6   598.4 1569.36   608.3 1574.56
   618.3 1578.04   628.3 1580.06   638.2 1580.74   648.2 1580.82   658.2 1581.73
     728 1596.28   767.9 1605.27   817.7 1619.43   857.6 1632.82   887.6 1644.28
   987.3 1684.97   997.2 1688.77  1007.2 1691.88  1017.2 1693.69    1067  1697.7
#Mann= 3 , 0 , 0
       0      .1       0   537.7    .045       0   552.7      .1       0
Bank Sta=537.7,552.7
XS Rating Curve= 0 ,0
Exp/Cntr=0.3,0.1

Type RM Length L Ch R = 1 ,3750.9  ,235.1,236.7,237.4
XS GIS Cut Line= 2
     1958555.742      364700.367     1959138.829      364589.079
#Sta/Elev= 30
       0 1604.77    29.7 1596.43   128.6 1570.39   138.5 1567.53   148.4 1563.84
   158.3 1558.88   178.1 1547.06   227.6 1515.98   247.3  1502.7   257.2  1497.3
   267.1 1495.22     277 1495.45   286.9 1496.26   336.4  1500.3   346.3 1503.11
   356.2 1508.47   366.1 1515.22   425.4 1558.12   435.3 1563.47   445.2 1566.02
   455.1 1566.63   474.9 1566.65   484.8 1567.24   494.7 1569.73   504.6  1574.3
   514.5 1579.88   544.1 1597.79   563.9 1609.16   583.7 1619.06   593.6 1622.78
#Mann= 3 , 0 , 0
       0      .1       0   267.1    .045       0   286.9      .1       0
Bank Sta=267.1,286.9
XS Rating Curve= 0 ,0
Exp/Cntr=0.3,0.1

Type RM Length L Ch R = 1 ,3514    ,199.8,198.8,198.8
XS GIS Cut Line= 3
     1958331.949      364942.731     1958877.675      364879.925
     1959415.548      364791.122
#Sta/Elev= 30
       0 1663.23    49.9 1647.12    89.9 1636.53   129.8  1627.3   189.8 1616.52
   209.7 1610.75   369.6 1556.18   499.4 1499.64   529.4 1484.83   539.3 1482.62
   541.8 1482.74   549.3 1483.08   556.8 1484.21   579.1 1489.34     589 1492.66
   598.9 1496.87   618.7 1507.76   658.4  1533.9   668.3 1539.86   678.2 1543.93
     698 1548.59   707.9 1551.73   737.6 1563.04   787.2  1583.4     807 1590.83
   826.9 1596.63   876.4 1609.17   906.2 1618.82   916.1 1621.34  1094.5 1655.53
#Mann= 3 , 0 , 0
       0      .1       0   541.8    .045       0   556.8      .1       0
Bank Sta=541.8,556.8
XS Rating Curve= 0 ,0
Exp/Cntr=0.3,0.1

Type RM Length L Ch R = 1 ,3315.2  ,129.3,129.7,130.1
XS GIS Cut Line= 2
     1958709.025      365107.379     1959072.279        365048.6
#Sta/Elev= 30
       0  1538.9      10  1534.4    19.9 1531.88    29.8 1530.53    39.8 1528.84
    49.7 1526.44    69.6 1521.19    79.6 1518.26    89.5 1514.98    99.4 1511.42
   109.4  1507.6   119.3 1503.53   159.1  1486.5     179 1477.18   183.6 1476.01
     189 1474.64   198.6 1475.01   208.8  1477.8   218.8 1481.38   238.7 1487.76
   248.6 1491.51   258.6 1495.69   278.5  1504.7   298.4 1514.31   318.2 1526.21
   328.2 1530.11   338.1 1533.04   348.1 1538.15     358 1545.43     368 1553.47
#Mann= 3 , 0 , 0
       0      .1       0   183.6    .045       0   198.6      .1       0
Bank Sta=183.6,198.6
XS Rating Curve= 0 ,0
Exp/Cntr=0.3,0.1

Type RM Length L Ch R = 1 ,3185.3  ,129,127.9,126.9
XS GIS Cut Line= 2
     1958396.222       365278.77     1959162.341      365165.896
#Sta/Elev= 30
       0 1652.47    19.9 1643.33    39.7 1636.08    69.5 1629.78   119.1  1623.6
   208.5 1619.89   238.3 1617.21   248.2 1613.36   268.1 1599.32   287.9 1582.53
   327.6 1545.42   347.5 1530.46   357.4 1525.91   367.3 1523.48     407 1518.41
     417 1516.12   506.3 1481.26   536.1 1468.05   540.9 1466.75     546 1465.36
   555.9 1465.21   575.8 1468.13   585.8 1471.26   595.7 1476.54   625.5 1496.19
   655.2 1513.22   675.1 1519.77     685 1524.12   724.8 1544.98   774.4  1568.7
#Mann= 3 , 0 , 0
       0      .1       0   540.9    .045       0   555.9      .1       0
Bank Sta=540.9,555.9
XS Rating Curve= 0 ,0
Exp/Cntr=0.3,0.1

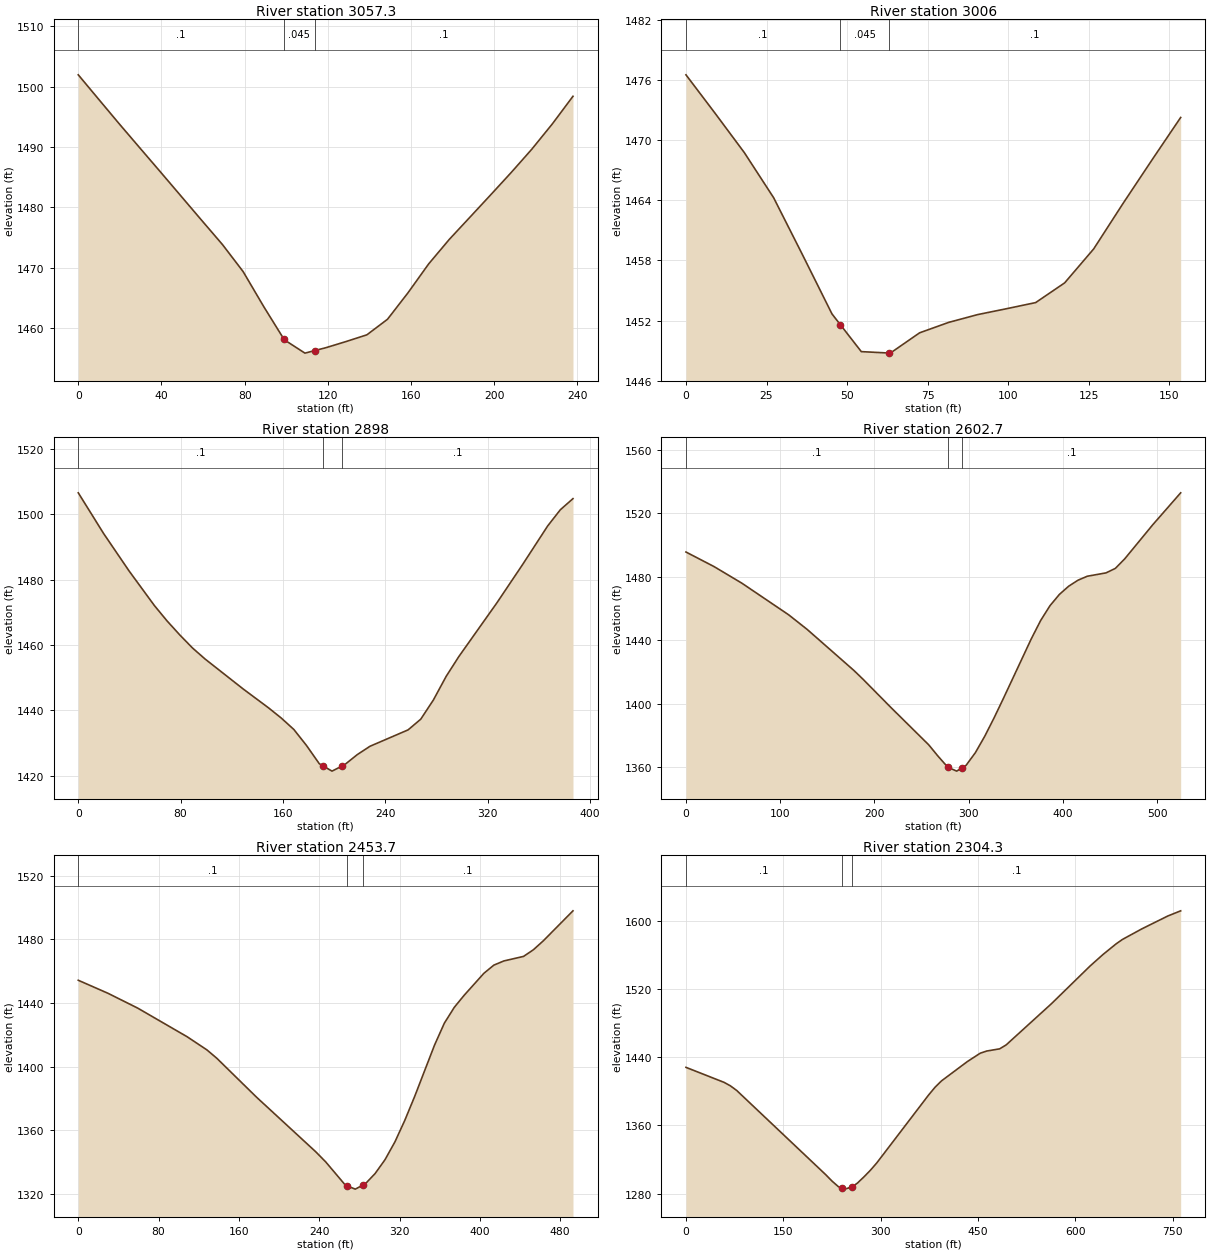
Type RM Length L Ch R = 1 ,3057.3  ,52,50.6,43.5
XS GIS Cut Line= 2
     1958847.286      365346.152     1959080.834      365300.696
#Sta/Elev= 27
       0 1501.94     9.9 1497.86    19.8 1493.79    29.7 1489.81    39.7  1485.8
    49.6  1481.8    59.5  1477.8    69.4 1473.83    79.3 1469.37    89.2 1463.58
    98.7 1458.31    99.1 1458.09     109 1455.89   113.7 1456.31     119 1456.78
   128.9 1457.82   138.8 1458.92   148.7 1461.49   158.6 1465.89   168.5 1470.65
   178.4  1474.7   188.4  1478.4   198.3 1482.07   208.2 1485.78   218.1 1489.63
     228 1493.83   237.9 1498.39
#Mann= 3 , 0 , 0
       0      .1       0    98.7    .045       0   113.7      .1       0
Bank Sta=98.7,113.7
XS Rating Curve= 0 ,0
Exp/Cntr=0.3,0.1

Type RM Length L Ch R = 1 ,3006    ,120.4,108.4,101.8
XS GIS Cut Line= 3
     1958894.728      365389.387     1958965.263      365372.635
     1959028.744      365322.379
#Sta/Elev= 20
       0 1476.55     9.1 1472.68    18.1 1468.78    27.2 1464.27    36.2 1458.54
    45.3 1452.66    47.9 1451.58    54.4 1448.89    62.9 1448.75    63.4 1448.74
    72.5 1450.77    81.5 1451.81    90.5 1452.59    99.5 1453.18   108.5 1453.79
   117.5 1455.76   126.5 1459.15   135.5 1463.64   144.5    1468   153.5 1472.29
#Mann= 3 , 0 , 0
       0      .1       0    47.9    .045       0    62.9      .1       0
Bank Sta=47.9,62.9
XS Rating Curve= 0 ,0
Exp/Cntr=0.3,0.1

Type RM Length L Ch R = 1 ,2898    ,311.5,295,279
XS GIS Cut Line= 2
     1958855.123      365604.779      1959126.29       365328.91
#Sta/Elev= 30
       0 1506.58    19.8 1494.13    39.7 1482.68    59.5 1472.08    69.4 1467.38
    79.4 1463.07    89.3 1459.09    99.2 1455.69   128.9 1446.55   148.8 1440.75
   158.7 1437.64   168.6 1434.12   178.5 1429.21   188.4 1423.68     191 1423.08
   198.4 1421.39     206  1422.9   208.3 1423.36   218.2 1426.46   228.1    1429
   257.9 1434.02   267.8  1437.3   277.7 1443.19   287.6 1450.37   297.6 1456.48
   327.3  1472.9   347.2  1484.5     367 1496.43   376.9 1501.39   386.8  1504.8
#Mann= 3 , 0 , 0
       0      .1       0     191    .045       0     206      .1       0
Bank Sta=191,206
XS Rating Curve= 0 ,0
Exp/Cntr=0.3,0.1

Type RM Length L Ch R = 1 ,2602.7  ,146.9,149,151
XS GIS Cut Line= 2
     1959241.299      365862.117     1959276.764      365338.315
#Sta/Elev= 30
       0  1495.7    29.7 1486.56    59.4 1476.04     109 1456.14   128.8 1446.86
   178.3 1421.05   188.2 1415.38   217.9 1397.53   257.6 1374.26   267.4 1367.17
   277.9 1360.11   287.3 1357.68   292.9 1359.72   297.2 1361.29   307.1 1369.29
     317 1379.58   326.9 1391.13   336.8 1403.39   366.5 1441.06   376.4 1452.56
   386.3 1461.89   396.2 1468.94   406.1 1474.15     416 1477.94   425.9 1480.45
   445.8 1482.56   455.7  1485.4   465.6 1491.39   495.3 1512.83     525 1532.99
#Mann= 3 , 0 , 0
       0      .1       0   277.9    .045       0   292.9      .1       0
Bank Sta=277.9,292.9
XS Rating Curve= 0 ,0
Exp/Cntr=0.3,0.1

Type RM Length L Ch R = 1 ,2453.7  ,147.5,149.4,152.7
XS GIS Cut Line= 2
     1959363.735      365866.149     1959442.194      365379.699
#Sta/Elev= 30
       0 1454.25    29.6 1446.06    59.1 1436.79   108.4 1418.77   128.1 1410.51
     138 1405.23   177.4 1380.88   236.5  1346.5   246.4 1340.16   266.1 1325.47
   268.1 1324.97   275.9 1323.03   283.1 1325.42   285.8 1326.31   295.6 1332.79
   305.5 1341.53   315.4 1352.75   325.2 1366.23   335.1 1381.36   354.8 1413.49
   364.6  1427.3   374.5 1437.24   384.3 1444.79     404 1458.64   413.9 1463.76
   423.8 1466.37   443.5 1469.24   453.3 1473.42   463.2 1479.05   492.7 1497.87
#Mann= 3 , 0 , 0
       0      .1       0   268.1    .045       0   283.1      .1       0
Bank Sta=268.1,283.1
XS Rating Curve= 0 ,0
Exp/Cntr=0.3,0.1

Type RM Length L Ch R = 1 ,2304.3  ,294.8,300,302.3
XS GIS Cut Line= 3
     1959483.913      365893.349     1959545.047      365646.558
     1959708.974      365165.598
#Sta/Elev= 30
       0  1428.1    58.7 1410.51    68.4 1406.46    78.2 1400.99   215.1 1302.45
   224.9 1294.88   234.7  1288.3   240.6  1286.5   244.5 1285.31   255.6 1287.71
   264.2 1292.37   274.2  1299.6   284.1 1307.32   294.1 1316.08   373.8 1395.56
   383.8 1404.72   393.7 1412.18   433.6 1434.86   453.5  1444.7   463.5 1447.24
   483.4 1449.81   493.4 1454.41   563.1 1502.64   622.9 1547.03   642.8 1560.52
   662.8 1572.85   672.7 1578.13   702.6 1590.52   742.4 1605.53   762.4 1611.66
#Mann= 3 , 0 , 0
       0      .1       0   240.6    .045       0   255.6      .1       0
Bank Sta=240.6,255.6
XS Rating Curve= 0 ,0
Exp/Cntr=0.3,0.1

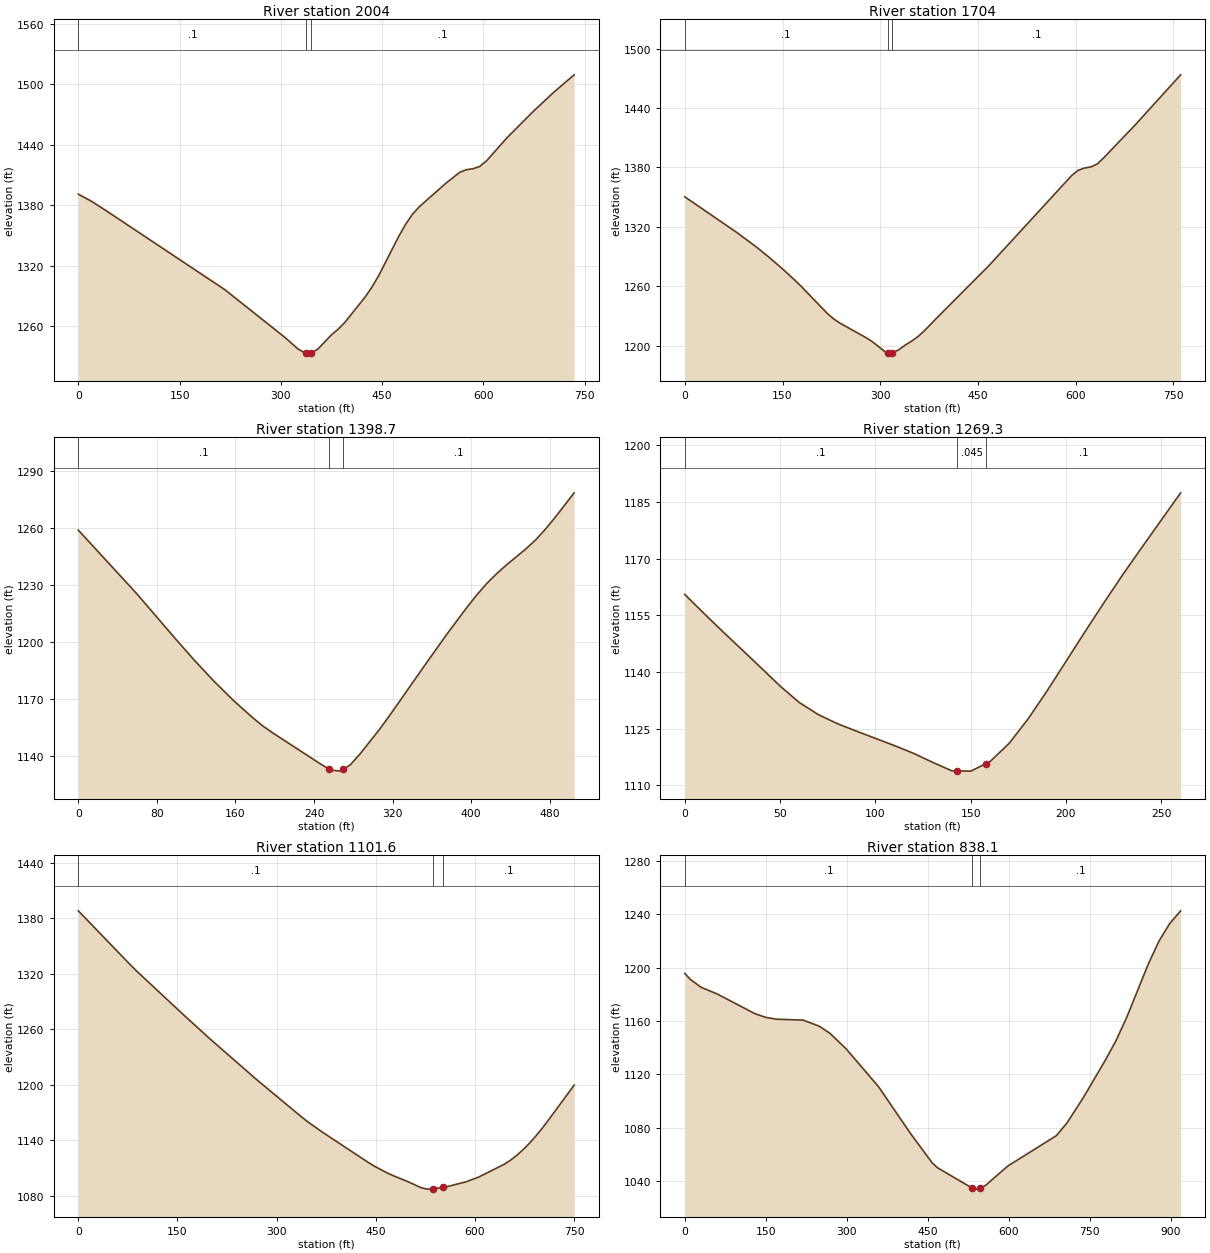
Type RM Length L Ch R = 1 ,2004    ,291.6,300,311
XS GIS Cut Line= 3
      1959678.54      366023.884     1959834.999       365716.25
     1959988.281      365358.591
#Sta/Elev= 30
       0 1390.98    19.7 1383.84    39.4 1375.38   216.9 1296.16   305.7 1248.82
   325.4  1237.2   335.3 1233.35   337.6 1233.28   345.1 1233.07   355.1 1237.31
   375.1 1251.42     385 1256.96     395 1263.84     425 1288.99   434.9 1298.75
   444.9  1310.1   474.8 1349.44   484.8  1361.1   494.8 1370.93   504.8  1378.4
   544.7 1402.04   564.6  1412.6   574.6  1415.3   584.6 1416.22   594.6 1418.59
   604.6 1424.14   634.5 1446.77   674.4 1473.61   704.3 1492.33   734.3 1509.52
#Mann= 3 , 0 , 0
       0      .1       0   337.6    .045       0   345.1      .1       0
Bank Sta=337.6,345.1
XS Rating Curve= 0 ,0
Exp/Cntr=0.3,0.1

Type RM Length L Ch R = 1 ,1704    ,308.2,305.1,300.9
XS GIS Cut Line= 3
     1959813.908      366129.945     1960051.948       365918.02
      1960396.63      365640.749
#Sta/Elev= 30
       0 1350.29    79.7 1314.34   109.6 1299.75   129.5 1289.12   149.4 1277.88
   169.3 1265.87   179.3 1259.43   219.1 1232.27   229.1 1226.67     239 1222.36
   278.9  1207.8   288.8 1203.52   308.8 1193.07   311.2 1192.91   318.7 1192.39
   328.5 1195.83   338.4 1200.56   348.2 1204.52     358 1209.13   367.9 1215.11
   387.5 1228.37   466.2 1280.35     594 1371.87   603.8 1377.08   613.6 1379.38
   623.4 1380.52   633.3 1383.58   643.1 1389.72   692.3  1423.6   761.1 1473.53
#Mann= 3 , 0 , 0
       0      .1       0   311.2    .045       0   318.7      .1       0
Bank Sta=311.2,318.7
XS Rating Curve= 0 ,0
Exp/Cntr=0.3,0.1

Type RM Length L Ch R = 1 ,1398.7  ,128.3,129.4,130.6
XS GIS Cut Line= 2
     1960066.753       366357.15     1960394.348      365973.127
#Sta/Elev= 30
       0 1259.05    59.4 1225.59      99 1201.72   118.8 1190.09   138.6 1179.16
   158.4 1169.07   178.2  1159.9     188 1155.78     198 1152.18   247.4 1135.55
   254.9  1133.3   257.3 1132.58   267.2 1132.05   269.9 1132.98   277.1 1135.47
     287 1141.24   306.8 1154.16   316.7 1161.19   356.3 1190.46   376.1 1204.82
   395.9 1218.52   405.8 1224.96   415.7 1230.87   425.6 1235.95   435.5 1240.55
   455.3 1248.99   465.2 1253.69   475.1 1259.27     485 1265.45   504.8  1278.7
#Mann= 3 , 0 , 0
       0      .1       0   254.9    .045       0   269.9      .1       0
Bank Sta=254.9,269.9
XS Rating Curve= 0 ,0
Exp/Cntr=0.3,0.1

Type RM Length L Ch R = 1 ,1269.3  ,164.6,167.7,160.7
XS GIS Cut Line= 2
     1960242.567      366337.818      1960420.21      366147.635
#Sta/Elev= 29
       0 1160.54      10 1155.54      20 1150.67      30 1145.91      40 1141.12
      50 1136.29    60.1 1131.92    70.1 1128.71    80.1 1126.32    90.1 1124.34
   100.1 1122.42   110.1  1120.5   120.1 1118.46   130.1 1116.08   140.1 1113.85
   143.1 1113.82   150.1 1113.76   158.1 1115.77   160.2  1116.3   170.2  1121.1
   180.2 1127.61   190.2 1135.06   200.2 1142.92   210.2  1150.8   220.2 1158.52
   230.2 1166.04   240.2 1173.22   250.2 1180.32   260.2 1187.43
#Mann= 3 , 0 , 0
       0      .1       0   143.1    .045       0   158.1      .1       0
Bank Sta=143.1,158.1
XS Rating Curve= 0 ,0
Exp/Cntr=0.3,0.1

Type RM Length L Ch R = 1 ,1101.6  ,272.1,263.5,265
XS GIS Cut Line= 3
     1960034.097      366691.636     1960468.017      366341.475
     1960491.529      366150.248
#Sta/Elev= 30
       0 1388.18    79.6 1329.16    89.6 1322.14   159.3 1275.66   199.1 1249.79
   268.8  1206.3   338.5 1164.93   348.5 1159.39   368.4 1149.35   438.1 1116.42
   448.1 1112.02     468 1104.53   477.9 1101.42   497.8 1095.64   517.8  1089.1
   527.7 1087.29   537.1 1087.47   552.1 1089.24   557.6 1089.93   586.5 1095.15
   605.8 1100.33   644.3 1114.14   653.9 1118.57   663.6 1123.97   673.2 1130.14
   682.8 1137.08   692.4 1144.83   702.1 1153.32   711.7 1162.33   750.2 1199.73
#Mann= 3 , 0 , 0
       0      .1       0   537.1    .045       0   552.1      .1       0
Bank Sta=537.1,552.1
XS Rating Curve= 0 ,0
Exp/Cntr=0.3,0.1

Type RM Length L Ch R = 1 ,838.1   ,346.9,336.5,326.2
XS GIS Cut Line= 3
     1960415.092      366958.715     1960693.728      366463.736
     1960715.673      366114.197
#Sta/Elev= 30
       0 1195.67      10 1191.29    29.9 1185.32    59.8  1180.3   129.6 1165.57
   149.5 1162.79   169.4 1161.39   219.2 1160.69   249.1 1156.13   269.1 1150.72
     299  1139.1   358.8 1110.83   418.5 1075.53   458.4 1053.69   468.4 1050.06
   532.4  1034.9   538.1 1034.15   547.4 1034.69     558  1037.3     598 1051.38
   688.1  1074.2   708.1 1083.88   738.1  1102.7   778.2 1130.28   798.2 1145.06
   818.2 1162.57   858.2 1202.54   878.2 1219.91   898.2  1233.1   918.2 1242.52
#Mann= 3 , 0 , 0
       0      .1       0   532.4    .045       0   547.4      .1       0
Bank Sta=532.4,547.4
XS Rating Curve= 0 ,0
Exp/Cntr=0.3,0.1

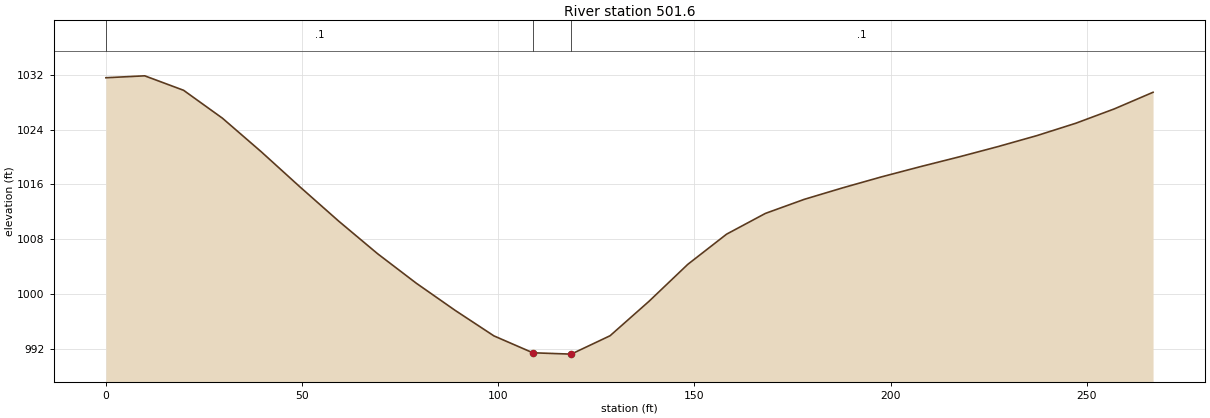
Type RM Length L Ch R = 1 ,501.6   ,489.2,501.1,513.1
XS GIS Cut Line= 2
     1960986.846      366716.196     1961000.946      366449.629
#Sta/Elev= 30
       0 1031.56     9.9 1031.84    19.8 1029.73    29.7 1025.66    39.6 1020.76
    49.4 1015.67    59.3 1010.66    69.2 1005.91    79.1 1001.59      89  997.63
    98.9   993.9   108.8  991.44   112.1  991.37   118.6  991.24   127.1  993.54
   128.5  993.92   138.4  998.93   148.3 1004.33   158.2 1008.74   168.1 1011.77
     178 1013.82   187.8  1015.5   197.7  1017.1   207.6 1018.59   217.5 1020.02
   227.4 1021.52   237.3 1023.12   247.2 1024.92     257 1027.01   266.9 1029.44
#Mann= 3 , 0 , 0
       0      .1       0   108.8    .045       0   118.6      .1       0
Bank Sta=108.8,118.6
XS Rating Curve= 0 ,0
Exp/Cntr=0.3,0.1

Chan Stop Cuts=-1
Use User Specified Reach Order=0
Composite Channel Slope=5